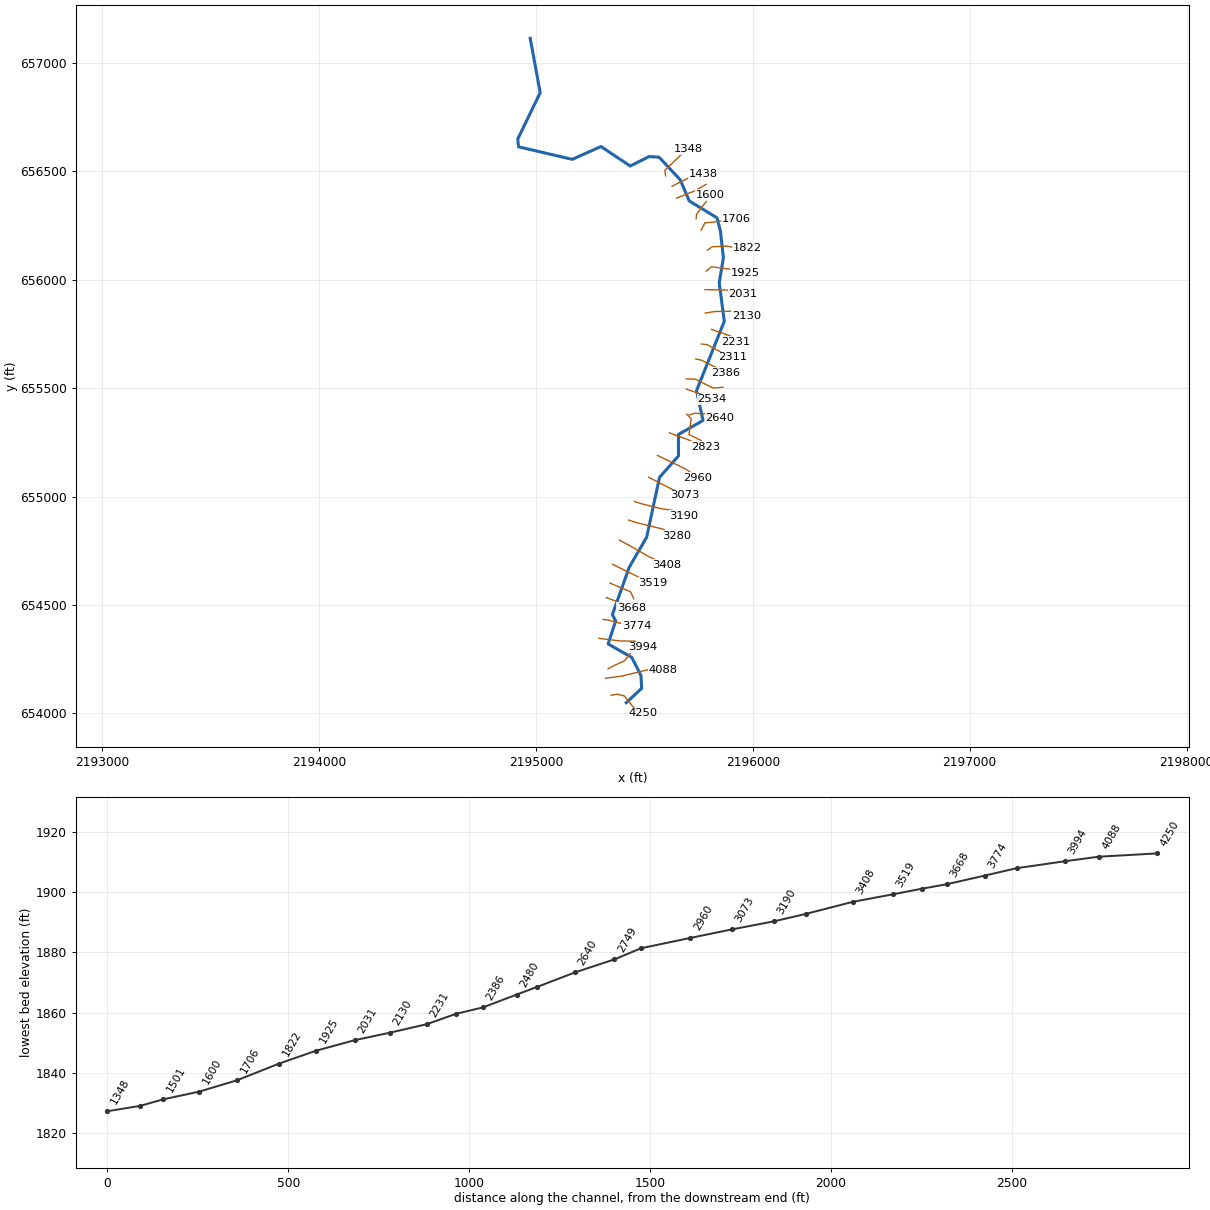
--- HERODSRN.prj (project) ---

Proj Title=HERODSRN
Current Plan=p01
Default Exp/Contr=0,0
English Units
Geom File=g01
Flow File=f01
Plan File=p01
BEGIN DESCRIPTION:
---------- MODELED AS PART OF WVEMD CTP PROGRAM, 2023----------
Stream Name: Herods Run
Flood Zone:  AFH
Upshur County, WV
HEC-RAS Version: RAS 6.3
Vertical Datum: NAVD88
Projection: NAD 1983 StatePlane West Virginia S FIPS 4702 (US Feet)
Terrain: 1-meter LIDAR (FEMA Region III 3DEP collected 2016-2018)
Land Use: 2019 NLCD
Hydrologic Method:
WV SIR2010-5033 regression equations
Additional Model Notes:
None
END DESCRIPTION:
DSS Export Rating Curves= 0
DSS Export Rating Curve Sorted= 0
DSS Export Volume Flow Curves= 0
DXF OffsetX= 0
DXF OffsetY= 0
DXF ScaleX= 0
DXF ScaleY= 0

--- HERODSRN.p01 (plan) ---

Plan Title=Floodplain
Program Version=6.30
Short Identifier=Floodplain
Geom File=g01
Flow File=f01
Subcritical Flow
K Sum by GR= 0
Std Step Tol= 0.01
Critical Tol= 0.01
Num of Std Step Trials= 20
Max Error Tol= 0.3
Flow Tol Ratio= 0.001
Split Flow NTrial= 30
Split Flow Tol= 0.02
Split Flow Ratio= 0.02
Log Output Level= 0
Friction Slope Method= 1
Unsteady Friction Slope Method= 2
Unsteady Bridges Friction Slope Method= 1
Parabolic Critical Depth
Global Vel Dist= 0 , 0 , 0
Global Log Level= 0
CheckData=False
Encroach Param=-1 ,0,0, 0
Mapping Interval=1HOUR
Computation Time Step Use Courant=        0
Computation Time Step Use Time Series=    0
Computation Time Step Count To Double=0
Computation Time Step Max Doubling=0
Computation Time Step Max Halving=0
Computation Time Step Residence Courant=0
Run HTab= 0
Run UNet= 0
Run Sediment= 0
Run PostProcess= 0
Run WQNet= 0
Run RASMapper=-1
UNET Theta= 0
UNET Theta Warmup= 0
UNET ZTol= 0
UNET ZSATol= 0
UNET MxIter= 0
UNET Max Iter WO Improvement= 0
UNET MaxInSteps= 0
UNET DtIC= 0
UNET DtMin= 0
UNET MaxCRTS= 0
UNET WFStab= 0
UNET SFStab= 0
UNET WFX= 1
UNET SFX= 1
UNET Gravity=32.17405
UNET 1D Methodology=Finite Difference
UNET DSS MLevel= 1
UNET Pardiso=0
UNET DZMax Abort= 0
UNET Use Existing IB Tables= 0
UNET Froude Reduction=False
UNET Froude Limit= 0
UNET Froude Power= 0
UNET D1 Cores= 0
UNET WindReference=Eulerian
UNET WindDragFormulation=Hsu (1988)
UNET D2 Coriolis=0
UNET D2 Cores= 0
UNET D2 Theta= 1
UNET D2 Theta Warmup= 1
UNET D2 Z Tol= 0.01
UNET D2 Volume Tol= 0.01
UNET D2 Max Iterations= 20
UNET D2 Equation= 0
UNET D2 RampUpFraction=0.1
UNET D2 TimeSlices= 1
UNET D2 Turbulence Formulation=Non-Conservative (original)
UNET D2 Eddy Viscosity=0.3
UNET D2 Transverse Eddy Viscosity=0.1
UNET D2 Smagorinsky Mixing=0
UNET D2 BCVolumeCheck=0
UNET D2 Cores=0
UNET D2 SolverType=PARDISO (Direct)
UNET D2 Minimum Iterations= 3
UNET D2 Maximum Iterations= 30
UNET D2 Restart Number= 10
UNET D2 Relaxation Coeff=1.3
UNET D2 SOR Precondition Iterations= 10
UNET D2 ILUT Maximum Fill= 8
UNET D2 ILUT Tolerance=1E-08
UNET D2 Convergence Tolerance=0.00001
UNET D1D2 MaxIter= 0
UNET D1D2 ZTol=0.01
UNET D1D2 QTol=0.1
UNET D1D2 MinQTol=1
Write IC File= 0
Write IC File at Fixed DateTime=0
Write IC File at Sim End=0
Echo Input=False
Echo Parameters=False
Echo Output=False
Write Detailed= 0
HDF Write Warmup=0
HDF Write Time Slices=0
HDF Flush=0
HDF Compression= 1
HDF Chunk Size= 1
HDF Spatial Parts= 1
HDF Use Max Rows=0
HDF Fixed Rows= 1
Calibration Method= 0
Calibration Iterations= 20
Calibration Max Change=0.05
Calibration Tolerance=0.2
Calibration Maximum=1.5
Calibration Minimum=0.5
Calibration Optimization Method= 1
WQ AD Non Conservative
WQ ULTIMATE=-1
WQ Max Comp Step=1HOUR
WQ Output Interval=15MIN
WQ Output Selected Increments= 0
WQ Output face flow=0
WQ Output face velocity=0
WQ Output face area=0
WQ Output face dispersion=0
WQ Output cell volume=0
WQ Output cell surface area=0
WQ Output cell continuity=0
WQ Output cumulative cell continuity=0
WQ Output face conc=0
WQ Output face dconc_dx=0
WQ Output face courant=0
WQ Output face peclet=0
WQ Output face adv mass=0
WQ Output face disp mass=0
WQ Output cell mass=0
WQ Output cell source sink temp=0
WQ Output nsm pathways=0
WQ Output nsm derived pathways=0
WQ Create Restart=0
WQ Fixed Restart=0
WQ System Summary=0
WQ Write To DSS=0
Sorting and Armoring Iterations= 10
XS Update Threshold= 0.02
Bed Roughness Predictor= 0
Hydraulics Update Threshold= 0.02
Energy Slope Method= 1
Volume Change Method= 1
Sediment Retention Method= 0
Sediment TS Multiplier= 1
Warm Up Method= 0
XS Weighting Method= 0
Number of US Weighted Cross Sections= 1
Number of DS Weighted Cross Sections= 1
Upstream XS Weight=0
Main XS Weight=1
Downstream XS Weight=0
Number of DS XS's Weighted with US Boundary= 1
Upstream Boundary Weight= 1
Weight of XSs Associated with US Boundary= 0
Number of US XS's Weighted with DS Boundary= 1
Downstream Boundary Weight= 0.5
Weight of XSs Associated with DS Boundary= 0.5
Percentile Method= 0
Sediment Output Level= 3
Mass or Volume Output= 0
Output Increment Type= 1
Profile and TS Output Increment= 1
Transport Output Increment 1
XS Output Flag= 0
XS Output Increment= 10
Read HDF5 Sediment Hotstart= 0
Sediment Hotstart Type= 0
Write Gradation File= 0
Read Gradation Hotstart= 0
Write HDF5 File= 1
Write Binary Output= 1
Write DSS Sediment File= 0
DSS Sediment Output Type= 1
SV Curve= 0
Specific Gage Flag= 0
Subcell Erosion Methods= 0
Subcell Deposition Methods= 0
Advection Scheme= 1
Matrix Solver= 0
Implicit Weighting Factor= 1
Maximum Outer Loop Convergence Iterations= 5
Convergence Maximum Absolute= 0.001
Convergence RMSE= 0.0001
Grain Fractions Max Abs Error= 0.001
Max Subgrid Regions= 1
Max Subgrid Length Scale= 3.402823E+38
Initial Layer Thickness= 3.402823E+38
Min Layer Thickness= 3.402823E+38
Max Layer Thickness= 3.402823E+38
Number of Layers= 5

--- HERODSRN.f01 (steady flow) ---

Flow Title=Flows
Program Version=6.30
Number of Profiles= 1
Profile Names=01pct
River Rch & RM=HERODSRN,Main,4250
     344
Boundary for River Rch & Prof#=HERODSRN,Main            , 1
Up Type= 0
Dn Type= 3
Dn Slope=0.022
DSS Import GetInterval= 0
DSS Import GetPeak= 0
DSS Import FillOption= 0

--- HERODSRN.g01 (geometry) ---

Geom Title=Geometry
Program Version=6.30

River Reach=HERODSRN        ,Main
Reach XY= 30
2195416.86188438654049.7632980642195487.79244269654115.737499551
2195484.38022014654175.6946475432195442.04441447 654258.24462438
     2195333.004       654320.172195367.93696266 654426.72387417
     2195352.778      654455.411     2195430.386      654674.126
     2195510.655      654812.057     2195570.148      655088.634
     2195657.457      655187.2752195657.31678263655286.125685925
     2195770.663      655350.675     2195740.587      655488.234
      2195868.76      655808.222     2195845.438      655985.586
     2195864.639      656100.796     2195851.018      656222.873
     2195835.307        656285.2     2195707.478       656362.75
      2195665.24      656460.819      2195568.03      656564.839
     2195521.987      656567.6722195435.26271741656523.910882104
     2195300.381      656613.802     2195167.744      656554.738
      2194920.27      656612.486     2194916.378      656648.399
     2195019.969      656862.106     2194973.954        657112.7

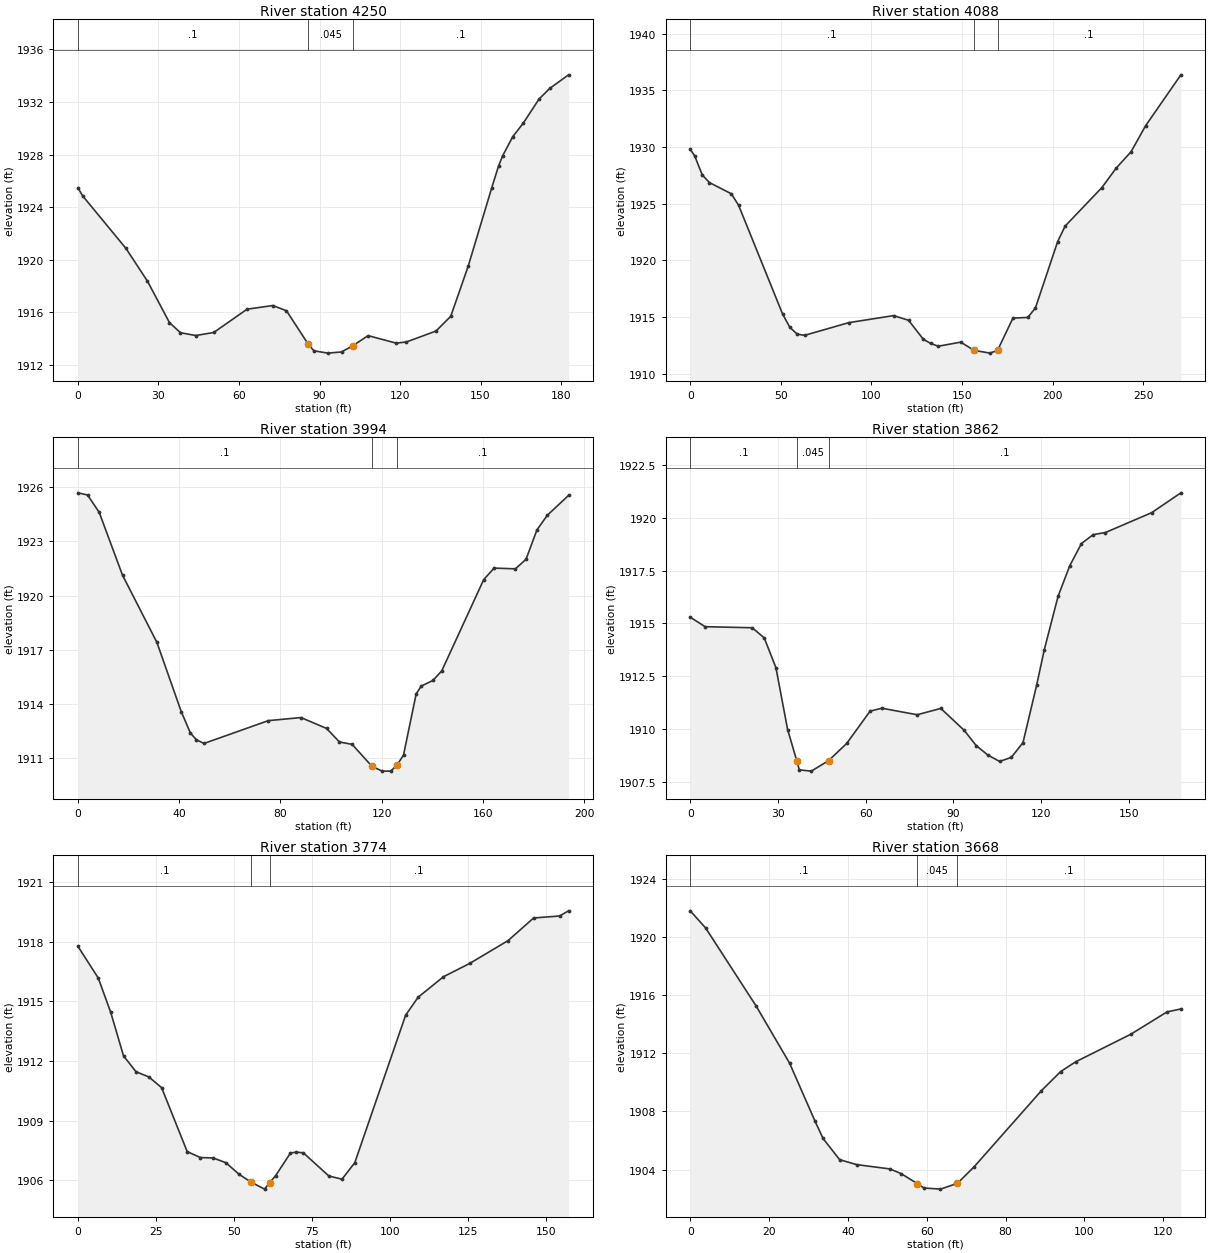
Type RM Length L Ch R = 1 ,4250    ,162.5,162.5,162.5
XS GIS Cut Line= 5
2195346.53557519 654084.02684691 2195375.9783842654088.595558652
2195408.46700103654080.4734044432195454.15411845654023.110690347
2195494.25725486654000.267131637
#Sta/Elev= 30
       0 1925.48     1.7 1924.88    17.9 1920.87    25.9 1918.38    34.1 1915.23
    38.2 1914.46    43.9 1914.25    50.6 1914.48      63 1916.25    72.6 1916.53
    77.7 1916.13    85.8 1913.59    87.9 1913.09    93.1 1912.91    98.2    1913
   102.4 1913.47   108.1 1914.24   118.6 1913.67   122.4 1913.76   133.4 1914.59
   138.9 1915.71   145.4 1919.52   154.2  1925.5   156.7 1927.13   158.2  1927.9
     162 1929.37   165.9 1930.39   171.8 1932.23   175.8 1933.04   182.8 1934.07
#Mann= 3 ,-1,0
       0      .1       0    85.8    .045       0   102.4      .1       0
Bank Sta=85.8,102.4
XS Rating Curve= 0 ,0
Exp/Cntr(USF)=0,0
Exp/Cntr=0.3,0.1

Type RM Length L Ch R = 1 ,4088    ,93.4,93.4,93.4
XS GIS Cut Line= 4
2195321.66147793654162.2025811642195395.56305388654172.023117928
2195532.32985271654205.3515253962195587.66202825654200.782813654
#Sta/Elev= 30
       0  1929.8     2.5  1929.2     6.6 1927.54    10.6 1926.86    22.7 1925.87
    26.7 1924.85      51 1915.25      55 1914.08      59 1913.49    63.1 1913.38
    87.5  1914.5   112.2 1915.12   120.5 1914.71   128.7 1913.02   132.8 1912.66
   136.9 1912.42   149.3 1912.78   156.61912.057   165.4 1911.81   169.61912.052
   178.1  1914.9   186.3 1914.96   190.5 1915.79   202.8 1921.66   206.9 1923.02
   227.2 1926.42   235.2 1928.16   243.3 1929.58   251.3 1931.87   270.8 1936.37
#Mann= 3 ,-1,0
       0      .1       0   156.6    .045       0   169.6      .1       0
Bank Sta=156.6,169.6
XS Rating Curve= 0 ,0
Exp/Cntr(USF)=0,0
Exp/Cntr=0.3,0.1

Type RM Length L Ch R = 1 ,3994    ,132.6,132.6,132.6
XS GIS Cut Line= 5
2195332.80481513654205.4900361712195359.00974356654219.954898251
2195409.52826983654243.1538640322195446.60878015654291.035316706
2195492.25798552 654304.96219292
#Sta/Elev= 30
       0 1925.68     3.8 1925.56     8.4  1924.6    17.6 1921.13    31.2 1917.41
    40.8 1913.59    44.4 1912.41    46.8 1912.03    49.8 1911.83    75.2 1913.09
    88.1 1913.26    98.2 1912.66   103.3 1911.91   108.3 1911.78  116.17 1910.56
   120.2  1910.3   123.5  1910.3     1261910.622   128.6 1911.19   133.6 1914.57
   135.6    1915   140.2 1915.31   143.7 1915.84   160.3 1920.89   164.4 1921.52
   172.8 1921.48     177 1922.01   181.3 1923.63   185.4 1924.44   193.8 1925.54
#Mann= 3 ,-1,0
       0      .1       0  116.17    .045       0     126      .1       0
Bank Sta=116.17,126
XS Rating Curve= 0 ,0
Exp/Cntr(USF)=0,0
Exp/Cntr=0.3,0.1

Type RM Length L Ch R = 1 ,3862    ,88,88,88
XS GIS Cut Line= 3
2195291.09199575654345.9691062192195388.58012925 654334.36337604
2195458.21451033 654332.81594535
#Sta/Elev= 30
       0 1915.29     5.1 1914.84    21.2 1914.79    25.3 1914.31    29.3  1912.9
    33.3 1909.97    36.51908.456    37.3 1908.06    41.4    1908    47.31908.496
    53.5 1909.31    61.5 1910.84    65.5 1910.98    77.6 1910.67    85.7 1910.97
    93.7 1909.93    97.8 1909.21   101.8 1908.76   105.8 1908.46   109.8 1908.65
   113.8 1909.35   118.5 1912.09   121.1 1913.76   125.8 1916.28   129.8 1917.73
   133.8 1918.78   137.8  1919.2     142  1919.3   157.8 1920.24   167.8 1921.18
#Mann= 3 ,-1,0
       0      .1       0    36.5    .045       0    47.3      .1       0
Bank Sta=36.5,47.3
XS Rating Curve= 0 ,0
Exp/Cntr(USF)=0,0
Exp/Cntr=0.3,0.1

Type RM Length L Ch R = 1 ,3774    ,106,106,106
XS GIS Cut Line= 5
2195309.69538927654433.2988292842195329.27195164654431.293301421
2195405.50547579654412.049887559 2195421.3797125654412.238671208
2195462.99113857654401.205152118
#Sta/Elev= 30
       0 1917.77     6.5 1916.18    10.5 1914.45    14.6 1912.26    18.6 1911.46
    22.7  1911.2    26.8 1910.66      35 1907.44    39.2 1907.14    43.3 1907.12
    47.4 1906.88    51.6  1906.3    55.6 1905.89    59.8 1905.55   61.39 1905.87
    63.3 1906.22    68.1 1907.37    69.9 1907.41    72.2 1907.38    80.4 1906.21
    84.6 1906.05    88.7 1906.88     105 1914.31     109 1915.21   117.1 1916.24
   125.5 1916.91   137.8 1918.06     146  1919.2   154.3  1919.3   157.2 1919.56
#Mann= 3 ,-1,0
       0      .1       0    55.6    .045       0   61.39      .1       0
Bank Sta=55.6,61.39
XS Rating Curve= 0 ,0
Exp/Cntr(USF)=0,0
Exp/Cntr=0.3,0.1

Type RM Length L Ch R = 1 ,3668    ,68.3,68.3,68.3
XS GIS Cut Line= 3
2195324.52855751654534.1145406112195413.52129652654501.525650269
2195439.21638314654486.484623957
#Sta/Elev= 21
       0 1921.82     3.9 1920.64    16.7 1915.27    25.2 1911.33    31.6 1907.37
    33.7 1906.14    37.9 1904.68    42.2 1904.34    50.7 1904.04    53.5 1903.72
    57.61903.034    59.3 1902.73    63.5 1902.65    67.8 1903.05      72 1904.18
    89.1 1909.43      94 1910.75    97.8 1911.42   111.8 1913.32     121 1914.86
   124.5 1915.06
#Mann= 3 ,-1,0
       0      .1       0    57.6    .045       0    67.8      .1       0
Bank Sta=57.6,67.8
XS Rating Curve= 0 ,0
Exp/Cntr(USF)=0,0
Exp/Cntr=0.3,0.1

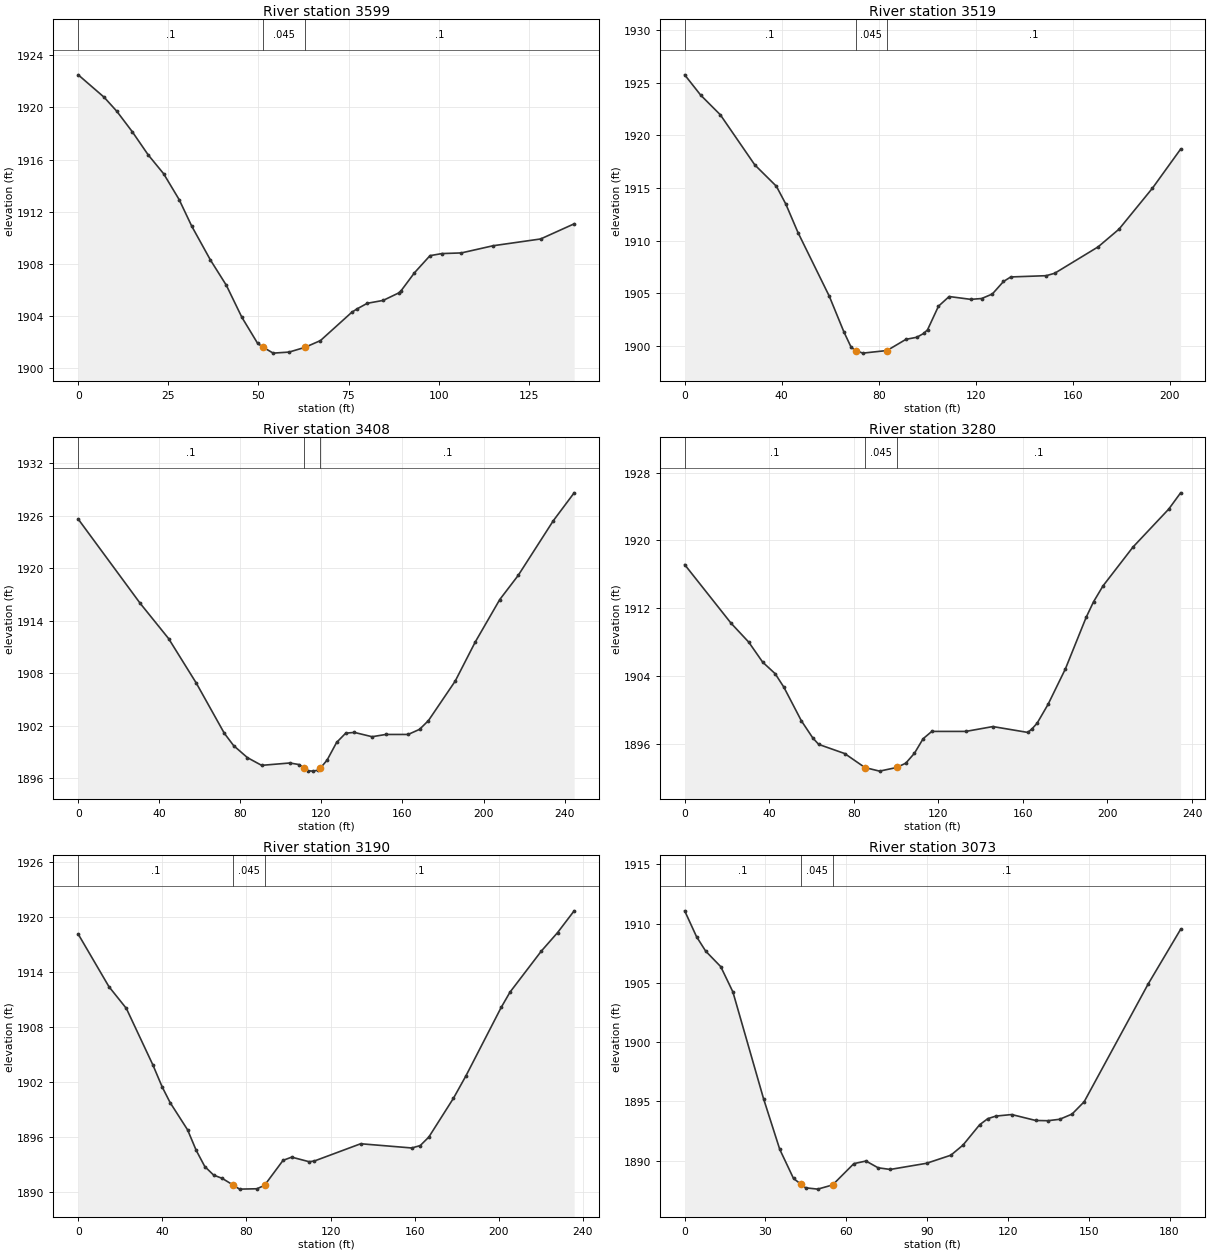
Type RM Length L Ch R = 1 ,3599    ,80.1,80.1,80.1
XS GIS Cut Line= 3
2195342.37266014654600.7581331642195436.76593226654560.524935211
2195451.46652382654528.802606055
#Sta/Elev= 30
       0  1922.5     7.2 1920.78    10.7 1919.71      15 1918.14    19.4 1916.37
    23.7 1914.92      28 1912.94    31.5  1910.9    36.7  1908.3    41.1 1906.37
    45.4 1903.92    49.8 1901.91    51.41901.605    54.1 1901.17    58.5 1901.25
    62.91901.612    67.2 1902.13    75.9  1904.3    77.3 1904.55    80.2 1904.99
    84.6 1905.21    88.9 1905.78    89.5 1905.92    93.3 1907.33    97.6 1908.64
   100.9  1908.8   106.3 1908.85   115.1  1909.4   128.3 1909.92   137.6 1911.08
#Mann= 3 ,-1,0
       0      .1       0    51.4    .045       0    62.9      .1       0
Bank Sta=51.4,62.9
XS Rating Curve= 0 ,0
Exp/Cntr(USF)=0,0
Exp/Cntr=0.3,0.1

Type RM Length L Ch R = 1 ,3519    ,110.8,110.8,110.8
XS GIS Cut Line= 3
2195354.20998473654686.933924356  2195486.877225654622.192311105
2195539.94412111654602.026890584
#Sta/Elev= 30
       0 1925.76     6.6 1923.83    14.7 1921.96    28.9  1917.2    37.8 1915.17
    41.7 1913.47    46.7 1910.77    59.6 1904.72    65.6 1901.34    68.6 1899.87
    70.51899.556    73.4 1899.31    83.41899.557    91.2 1900.62    95.7 1900.82
    98.5 1901.18   100.1 1901.53   104.6 1903.77     109 1904.69   117.9 1904.42
   122.4  1904.5   126.8 1904.93   131.4 1906.12   134.4 1906.55     149 1906.67
   152.5  1906.9   170.4 1909.41     179 1911.09   192.8 1914.99   204.4  1918.7
#Mann= 3 ,-1,0
       0      .1       0    70.5    .045       0    83.4      .1       0
Bank Sta=70.5,83.4
XS Rating Curve= 0 ,0
Exp/Cntr(USF)=0,0
Exp/Cntr=0.3,0.1

Type RM Length L Ch R = 1 ,3408    ,128.9,128.9,128.9
XS GIS Cut Line= 4
2195384.98878448654799.435744105 2195433.8103289654772.902296051
2195522.96271436654721.958075788 2195601.5017206654685.872586434
#Sta/Elev= 30
       0  1925.6    30.6 1915.97    44.6 1911.95    58.3 1906.85    72.1 1901.13
    76.7 1899.72    83.5 1898.35    90.5 1897.47   104.4 1897.74     109 1897.56
   111.4 1897.15   113.6 1896.85   115.7 1896.81   118.2 1896.91   119.5 1897.16
   122.8 1898.07   127.5 1900.09     132 1901.15   136.3 1901.23     145 1900.74
   151.8    1901   162.8    1901   168.4 1901.58   172.8 1902.58     186 1907.09
   195.9 1911.56     208 1916.41   217.1 1919.17   234.4 1925.41   244.7  1928.6
#Mann= 3 ,-1,0
       0      .1       0   111.4    .045       0   119.5      .1       0
Bank Sta=111.4,119.5
XS Rating Curve= 0 ,0
Exp/Cntr(USF)=0,0
Exp/Cntr=0.3,0.1

Type RM Length L Ch R = 1 ,3280    ,90.1,90.1,90.1
XS GIS Cut Line= 4
2195427.44230136654891.7721433332195462.46645279654880.097426189
2195583.45897592654850.3799643692195649.26192709654818.539826704
#Sta/Elev= 30
       0 1917.15    21.9 1910.26    30.3 1908.02    36.9 1905.66    42.8  1904.3
    46.9 1902.72    55.2 1898.75    60.6 1896.73    63.4 1895.97    75.7 1894.89
    85.31893.238    92.2 1892.82   100.3 1893.25   104.6 1893.76   108.7 1894.93
   112.8 1896.64   116.9  1897.5     133  1897.5   145.8 1898.07   162.3 1897.38
   164.3  1897.8   166.7 1898.46   171.9 1900.69   180.1 1904.87   189.9 1910.93
   193.4 1912.77   197.9 1914.65   212.1 1919.23     229  1923.7   234.6 1925.61
#Mann= 3 ,-1,0
       0      .1       0    85.3    .045       0   100.3      .1       0
Bank Sta=85.3,100.3
XS Rating Curve= 0 ,0
Exp/Cntr(USF)=0,0
Exp/Cntr=0.3,0.1

Type RM Length L Ch R = 1 ,3190    ,116.4,116.4,116.4
XS GIS Cut Line= 5
2195454.24466383654976.9374444662195487.52293454654966.784751705
  2195573.820823654944.7872507242195627.40447924654936.890711911
2195679.29602001 654911.50898001
#Sta/Elev= 30
       0 1918.12    14.6 1912.39    22.9 1910.01    35.5 1903.85    39.9 1901.46
    43.7 1899.74      52 1896.77    56.1 1894.53    60.2 1892.76    64.4 1891.83
    68.5 1891.47    73.61890.755    76.7  1890.3      85 1890.34    88.61890.718
    97.4 1893.44   101.5 1893.79   109.8 1893.29   112.3 1893.37   134.3 1895.25
   158.6 1894.79   162.6 1895.05   166.7 1895.98   178.4 1900.21   184.4 1902.68
   201.1 1910.12   205.3 1911.79   220.2 1916.27   227.9 1918.28   235.8 1920.66
#Mann= 3 ,-1,0
       0      .1       0    73.6    .045       0    88.6      .1       0
Bank Sta=73.6,88.6
XS Rating Curve= 0 ,0
Exp/Cntr(USF)=0,0
Exp/Cntr=0.3,0.1

Type RM Length L Ch R = 1 ,3073    ,113.6,113.6,113.6
XS GIS Cut Line= 3
2195520.27498756655088.7649109242195649.72182025655022.264773344
2195684.24097564655005.005195651
#Sta/Elev= 30
       0 1911.08     4.4  1908.9     7.8 1907.68    13.4 1906.37    17.9 1904.24
    29.3 1895.22    35.3 1890.96    40.4 1888.51    43.21888.018    44.9 1887.72
    49.4 1887.61    54.91887.963    62.8 1889.76    67.3 1889.98    71.8 1889.41
    76.3 1889.27    89.8 1889.79    98.8 1890.47   103.3 1891.32   109.5 1893.04
   112.5 1893.55   115.5 1893.77   121.4  1893.9   130.3  1893.4   134.8 1893.38
   139.2  1893.5   143.8 1893.94   148.3 1894.98     172 1904.89   184.1 1909.52
#Mann= 3 ,-1,0
       0      .1       0    43.2    .045       0    54.9      .1       0
Bank Sta=43.2,54.9
XS Rating Curve= 0 ,0
Exp/Cntr(USF)=0,0
Exp/Cntr=0.3,0.1

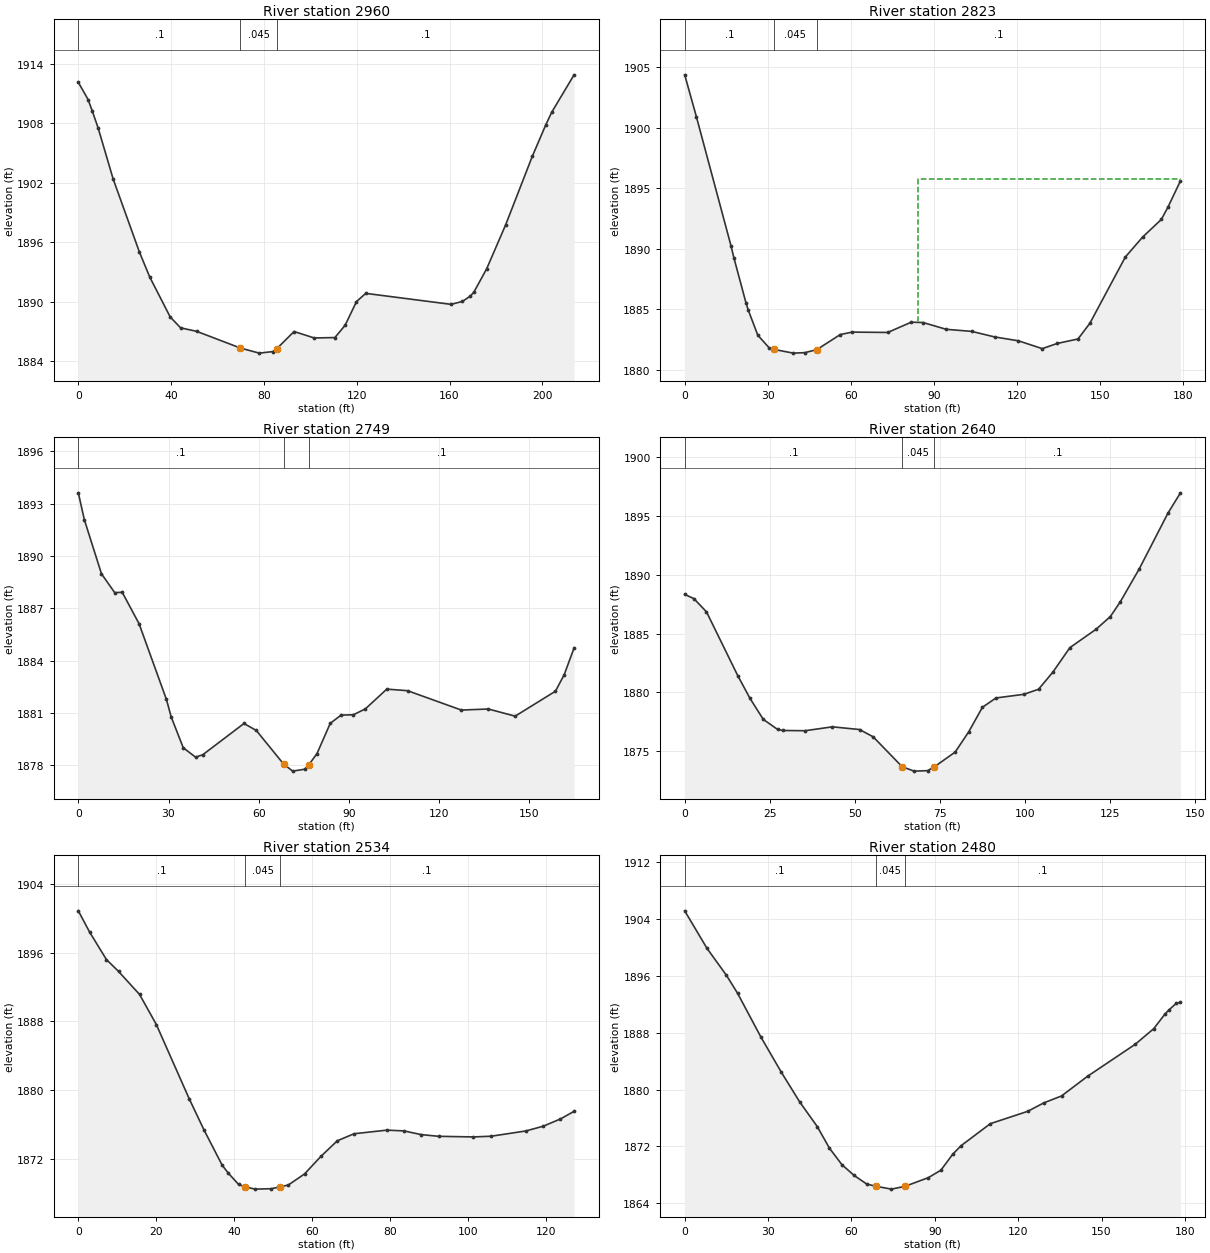
Type RM Length L Ch R = 1 ,2960    ,136.5,136.5,136.5
XS GIS Cut Line= 3
2195560.42486401655189.4056555392195691.33750043655126.734712573
 2195747.7413491655087.739459172
#Sta/Elev= 30
       0 1912.13     4.2  1910.4       6 1909.25     8.6 1907.48      15 1902.39
    26.3 1895.03    30.8 1892.48    39.6 1888.46    44.1 1887.36      51 1887.01
    69.91885.319      78 1884.81      84 1884.97    85.61885.269      93 1886.99
   101.7 1886.34   110.6 1886.38     115 1887.62   119.9 1890.01   123.9 1890.84
   160.7 1889.73   165.6 1890.03     169 1890.57   170.5 1890.96     176 1893.31
   184.2 1897.75   195.7 1904.67   201.5 1907.84   204.1 1909.13   213.7 1912.89
#Mann= 3 ,-1,0
       0      .1       0    69.9    .045       0    85.6      .1       0
Bank Sta=69.9,85.6
XS Rating Curve= 0 ,0
Exp/Cntr(USF)=0,0
Exp/Cntr=0.3,0.1

Type RM Length L Ch R = 1 ,2823    ,73.6,73.6,73.6
XS GIS Cut Line= 3
2195615.43602506655293.8572271482195692.73018805655265.307130908
2195782.55853963655229.793596561
#Sta/Elev= 30
       0 1904.39     4.2 1900.94    16.7 1890.26    17.8 1889.22    22.1 1885.55
    22.9 1884.96    26.4 1882.85    30.6 1881.78    32.2 1881.68    39.2 1881.37
    43.4 1881.41    47.7 1881.66    56.2 1882.91    60.5 1883.11    73.3 1883.08
    81.8 1883.93    86.1  1883.9    94.4 1883.34   103.6 1883.17   111.9 1882.71
   120.5 1882.39   129.1 1881.74   134.5 1882.17     142 1882.54   146.3 1883.84
   159.1 1889.32   165.3 1890.96   172.1 1892.43   174.5 1893.45     179 1895.62
#Mann= 3 ,-1,0
       0      .1       0    32.2    .045       0    47.7      .1       0
#XS Ineff= 2 , 0
                           84.39         1895.77
Permanent Ineff=
       F       F
Bank Sta=32.2,47.7
XS Rating Curve= 0 ,0
Exp/Cntr(USF)=0,0
Exp/Cntr=0.3,0.1

Type RM Length L Ch R = 1 ,2749    ,109.5,109.5,109.5
XS GIS Cut Line= 4
2195695.62697831  655379.52074642195716.28889185655358.728616559
2195705.96072045 655286.197445232195761.66822531655258.343692801
#Sta/Elev= 30
       0 1893.62       2 1892.08     7.7 1888.98    12.1  1887.9    14.6 1887.92
    20.2 1886.12    29.3 1881.78    30.9 1880.77    34.9 1879.01      39 1878.47
    41.4 1878.61    55.1  1880.4    59.2    1880    68.31878.071    71.3 1877.67
    75.3 1877.78    76.71878.041    79.4 1878.68    83.8 1880.41    87.4 1880.88
    91.5  1880.9    95.5 1881.24   102.6 1882.37   109.5 1882.28   127.4 1881.17
   136.4 1881.23   145.3 1880.82   158.7 1882.25   161.6 1883.19   164.9 1884.73
#Mann= 3 ,-1,0
       0      .1       0    68.3    .045       0    76.7      .1       0
Bank Sta=68.3,76.7
XS Rating Curve= 0 ,0
Exp/Cntr(USF)=0,0
Exp/Cntr=0.3,0.1

Type RM Length L Ch R = 1 ,2640    ,105.5,105.5,105.5
XS GIS Cut Line= 4
2195706.00112559655376.0077434562195733.57634049655384.154966041
2195800.00754004655379.7680000332195847.63745669655363.473554862
#Sta/Elev= 30
       0 1888.32     2.7 1887.96     6.4 1886.84    15.6 1881.42    19.2 1879.49
    23.1 1877.71    27.3 1876.86    28.8 1876.77    35.4 1876.75    43.4 1877.08
    51.4 1876.85    55.4 1876.23    63.91873.696    67.4 1873.32    71.4 1873.36
    73.4 1873.69    79.5 1874.94    83.5 1876.67    87.5 1878.74    91.5 1879.53
    99.7 1879.84     104 1880.27   108.2 1881.72   113.2  1883.8   120.9 1885.36
   125.1 1886.44     128 1887.68   133.6 1890.49     142  1895.2   145.7 1896.94
#Mann= 3 ,-1,0
       0      .1       0    63.9    .045       0    73.4      .1       0
Bank Sta=63.9,73.4
XS Rating Curve= 0 ,0
Exp/Cntr(USF)=0,0
Exp/Cntr=0.3,0.1

Type RM Length L Ch R = 1 ,2534    ,54.7,54.7,54.7
XS GIS Cut Line= 4
2195693.46693699 655495.709244522195713.52163874655488.188731364
2195769.29877798655469.3874484742195811.28830977655448.706037296
#Sta/Elev= 30
       0 1900.86     2.9 1898.38     7.2 1895.19    10.3 1893.81    15.7 1891.12
      20 1887.62    28.4    1879    32.2 1875.36    36.9 1871.22    38.5 1870.29
    41.1 1868.99    42.71868.735    45.3 1868.45    49.5  1868.5    51.81868.725
    53.8 1868.92      58 1870.22    62.2 1872.27    66.4 1874.08    70.7  1874.9
    79.1 1875.32    83.5 1875.23    87.9  1874.8    92.4  1874.6   101.3 1874.53
   105.8 1874.61   114.7 1875.22   119.2 1875.78   123.6 1876.62   127.1 1877.51
#Mann= 3 ,-1,0
       0      .1       0    42.7    .045       0    51.8      .1       0
Bank Sta=42.7,51.8
XS Rating Curve= 0 ,0
Exp/Cntr(USF)=0,0
Exp/Cntr=0.3,0.1

Type RM Length L Ch R = 1 ,2480    ,93.8,93.8,93.8
XS GIS Cut Line= 4
2195693.16858206655542.4290318032195734.53140442655541.175612944
2195819.13717742655499.8127905862195861.75341864655504.199756594
#Sta/Elev= 30
       0 1905.18       8 1899.91      15 1896.11      19 1893.59    27.4 1887.42
    34.8 1882.43    41.4 1878.26    47.7  1874.8    52.1 1871.75    56.6 1869.42
      61 1867.91    65.5 1866.71    68.7  1866.4    74.4 1865.99    79.31866.385
    87.7 1867.61    92.2 1868.66    96.4 1870.88    99.4 1872.09     110 1875.21
   123.4 1876.94   129.3 1878.15   135.6 1879.11     145 1881.89   162.1 1886.38
   168.8 1888.59   172.8 1890.63   174.2  1891.2   176.8 1892.13   178.4 1892.29
#Mann= 3 ,-1,0
       0      .1       0    68.7    .045       0    79.3      .1       0
Bank Sta=68.7,79.3
XS Rating Curve= 0 ,0
Exp/Cntr(USF)=0,0
Exp/Cntr=0.3,0.1

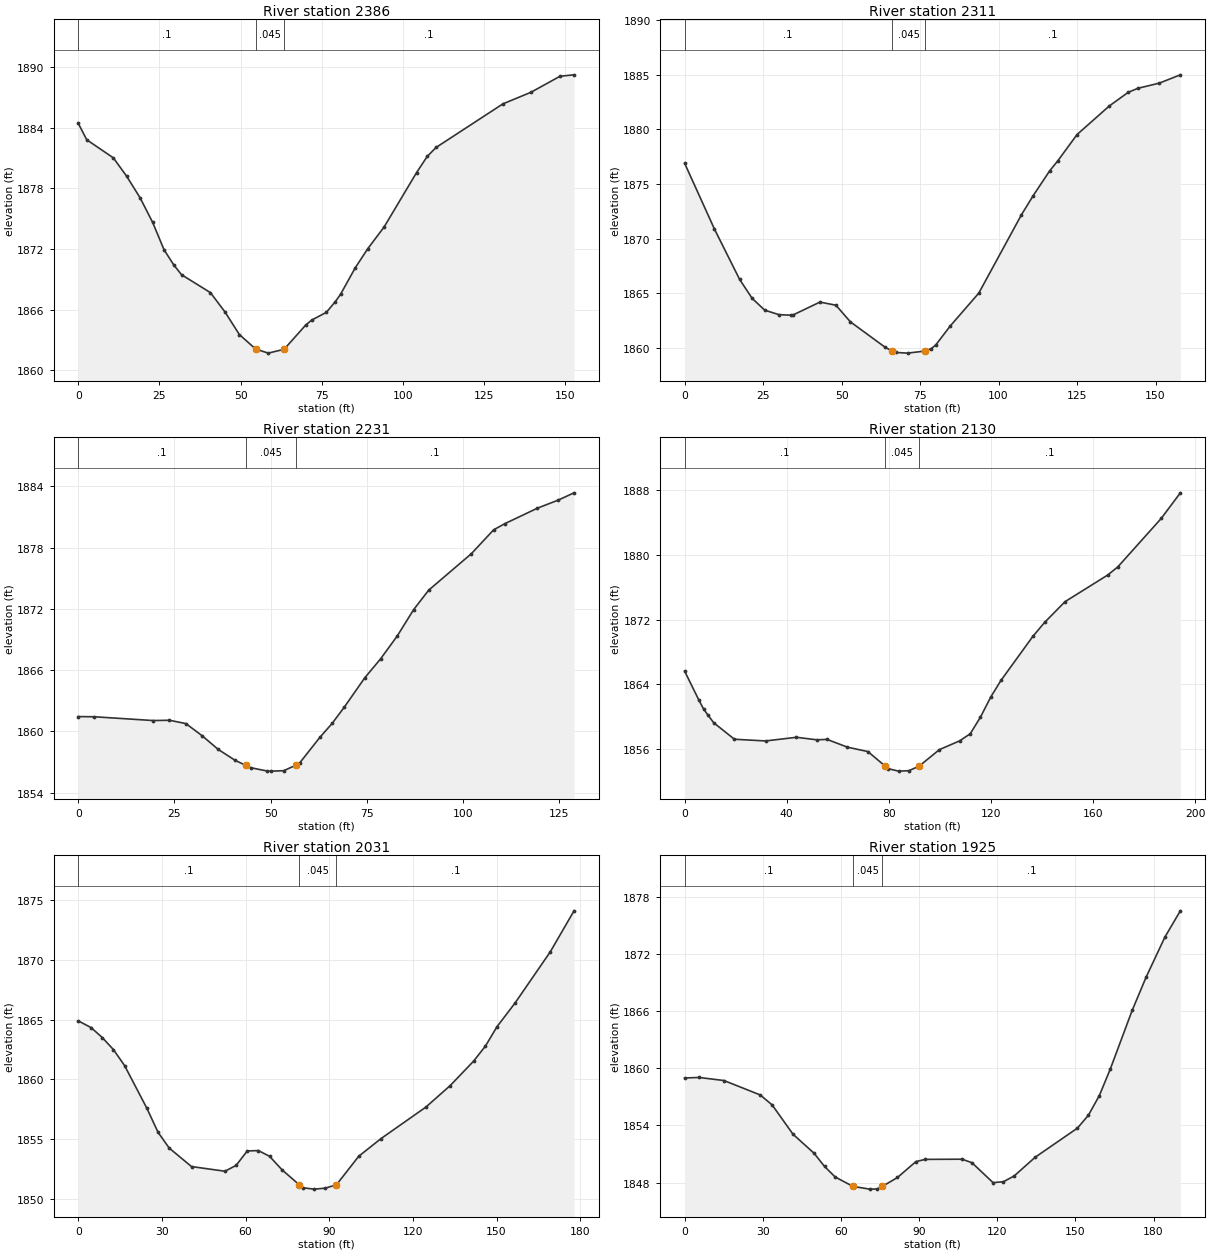
Type RM Length L Ch R = 1 ,2386    ,74.9,74.9,74.9
XS GIS Cut Line= 4
2195737.66495157655634.5553179622195762.10661933655628.914933095
2195844.20555461655588.8055295972195875.54102609655570.630956137
#Sta/Elev= 30
       0  1884.4     2.6 1882.79    10.8    1881    14.9 1879.18      19 1877.07
    22.9 1874.62    26.4 1871.92    29.4 1870.42    31.8 1869.45    40.7 1867.68
    45.2 1865.76    49.6 1863.54    54.61862.111    58.5  1861.7    63.4 1862.08
      70 1864.46    71.9 1864.97    76.4 1865.73    79.2  1866.8    80.8 1867.53
    85.3 1870.13    89.2 1872.04    94.2 1874.17   104.2 1879.55   107.5 1881.15
   110.2 1882.03   130.8 1886.34   139.4 1887.48   148.4 1889.07   152.7 1889.21
#Mann= 3 ,-1,0
       0      .1       0    54.6    .045       0    63.4      .1       0
Bank Sta=54.6,63.4
XS Rating Curve= 0 ,0
Exp/Cntr(USF)=0,0
Exp/Cntr=0.3,0.1

Type RM Length L Ch R = 1 ,2311    ,80.2,80.2,80.2
XS GIS Cut Line= 4
2195762.73332876655702.8666457942195788.42841537655700.986517505
2195864.88696579655659.6236951482195906.24978815655641.449121688
#Sta/Elev= 30
       0  1876.9     9.5 1870.88    17.5 1866.29    21.5 1864.55    25.5 1863.47
      30 1863.06    33.8 1863.01    34.6 1863.04    43.1 1864.21    48.2 1863.92
    52.8  1862.4    63.8 1860.09      661859.743    67.4  1859.6      71 1859.54
    76.61859.731    78.6 1859.96      80 1860.29    84.6 1862.02    93.7 1865.03
   107.3  1872.2     111 1873.93   116.3 1876.22   118.8  1877.1     125 1879.53
   135.3 1882.15   141.3 1883.39   144.4 1883.76   151.2 1884.23   157.9 1884.99
#Mann= 3 ,-1,0
       0      .1       0      66    .045       0    76.6      .1       0
Bank Sta=66,76.6
XS Rating Curve= 0 ,0
Exp/Cntr(USF)=0,0
Exp/Cntr=0.3,0.1

Type RM Length L Ch R = 1 ,2231    ,101,101,101
XS GIS Cut Line= 3
2195809.73653598655770.5512641972195895.59572784655741.095921003
2195923.17094275655714.774124958
#Sta/Elev= 29
       0 1861.46     4.2 1861.44    19.5 1861.07    23.7  1861.1      28 1860.77
    32.2 1859.58    36.4 1858.24    40.8 1857.17    43.51856.696    44.9 1856.45
    49.1 1856.13    50.2 1856.12    53.4 1856.16    56.5 1856.69    57.6 1856.94
    62.8 1859.42      66 1860.79    69.1 1862.35    74.5 1865.26    78.6 1867.11
    82.9 1869.33    87.2 1871.93    91.1 1873.83   102.2  1877.4     108 1879.74
   110.9 1880.34   119.4 1881.86   124.8 1882.65   128.9 1883.36
#Mann= 3 ,-1,0
       0      .1       0    43.5    .045       0    56.5      .1       0
Bank Sta=43.5,56.5
XS Rating Curve= 0 ,0
Exp/Cntr(USF)=0,0
Exp/Cntr=0.3,0.1

Type RM Length L Ch R = 1 ,2130    ,98.8,98.8,98.8
XS GIS Cut Line= 4
2195780.85632119655846.2644688332195825.97940013655853.158272559
2195904.94478826655854.4116914182195971.37598781655833.730280239
#Sta/Elev= 30
       0 1865.64     5.5 1862.12     7.4 1860.99       9 1860.28    11.4 1859.28
    19.5 1857.25    31.7 1857.04    43.8 1857.49    51.8 1857.18    55.8 1857.23
    63.8 1856.27    71.8 1855.73    78.51853.952    79.8 1853.62    83.8 1853.32
    87.8 1853.37    91.8 1853.92    99.8 1855.97   107.8 1857.06   111.9 1857.93
   115.9 1859.98   119.9 1862.44   123.9 1864.49   136.4 1869.92     141 1871.64
     149  1874.2   165.7 1877.48   169.7 1878.49   186.7 1884.46   194.2 1887.62
#Mann= 3 ,-1,0
       0      .1       0    78.5    .045       0    91.8      .1       0
Bank Sta=78.5,91.8
XS Rating Curve= 0 ,0
Exp/Cntr(USF)=0,0
Exp/Cntr=0.3,0.1

Type RM Length L Ch R = 1 ,2031    ,106,106,106
XS GIS Cut Line= 4
2195779.60290233655954.0584907332195846.03410188655952.805071874
2195895.54414682655951.5516530152195954.45483321655932.750370125
#Sta/Elev= 30
       0 1864.89     4.6 1864.32     8.6 1863.49    12.6 1862.48    16.6 1861.14
    24.6 1857.56    28.6 1855.55    32.6 1854.23    40.6 1852.68    52.6 1852.29
    56.6 1852.78    60.6 1853.99    64.6 1854.02    68.6 1853.54    73.1  1852.4
    79.21851.166    80.6  1850.9    84.6 1850.79    88.6 1850.87    92.6 1851.16
   100.6 1853.55   108.6 1855.03   124.7 1857.67   133.4 1859.47   141.8 1861.52
     146 1862.77   150.2 1864.41   156.6 1866.37   169.3 1870.68   177.8 1874.11
#Mann= 3 ,-1,0
       0      .1       0    79.2    .045       0    92.6      .1       0
Bank Sta=79.2,92.6
XS Rating Curve= 0 ,0
Exp/Cntr(USF)=0,0
Exp/Cntr=0.3,0.1

Type RM Length L Ch R = 1 ,1925    ,102.6,102.6,102.6
XS GIS Cut Line= 5
2195786.08643787656039.3966476382195809.76212743656059.590618149
2195877.30747707656050.5381486092195926.74788763656042.878366691
2195965.74314103656030.344178098
#Sta/Elev= 30
       0 1858.97     5.6 1859.02    15.1  1858.7      29 1857.19    33.6 1856.14
    41.6 1853.07    49.7 1851.07    53.7 1849.69    57.8 1848.58    64.6  1847.6
      71 1847.31    73.9 1847.32    75.91847.599    81.7 1848.53    88.8  1850.2
    92.4 1850.43   106.5 1850.45   110.3 1850.08   118.4 1847.99   122.4 1848.09
   126.5 1848.69   134.6 1850.66   150.8 1853.71     155 1855.06   159.2 1857.12
   163.4  1859.9   171.8 1866.05   177.2 1869.57   184.4 1873.76   190.3  1876.5
#Mann= 3 ,-1,0
       0      .1       0    64.6    .045       0    75.9      .1       0
Bank Sta=64.6,75.9
XS Rating Curve= 0 ,0
Exp/Cntr(USF)=0,0
Exp/Cntr=0.3,0.1

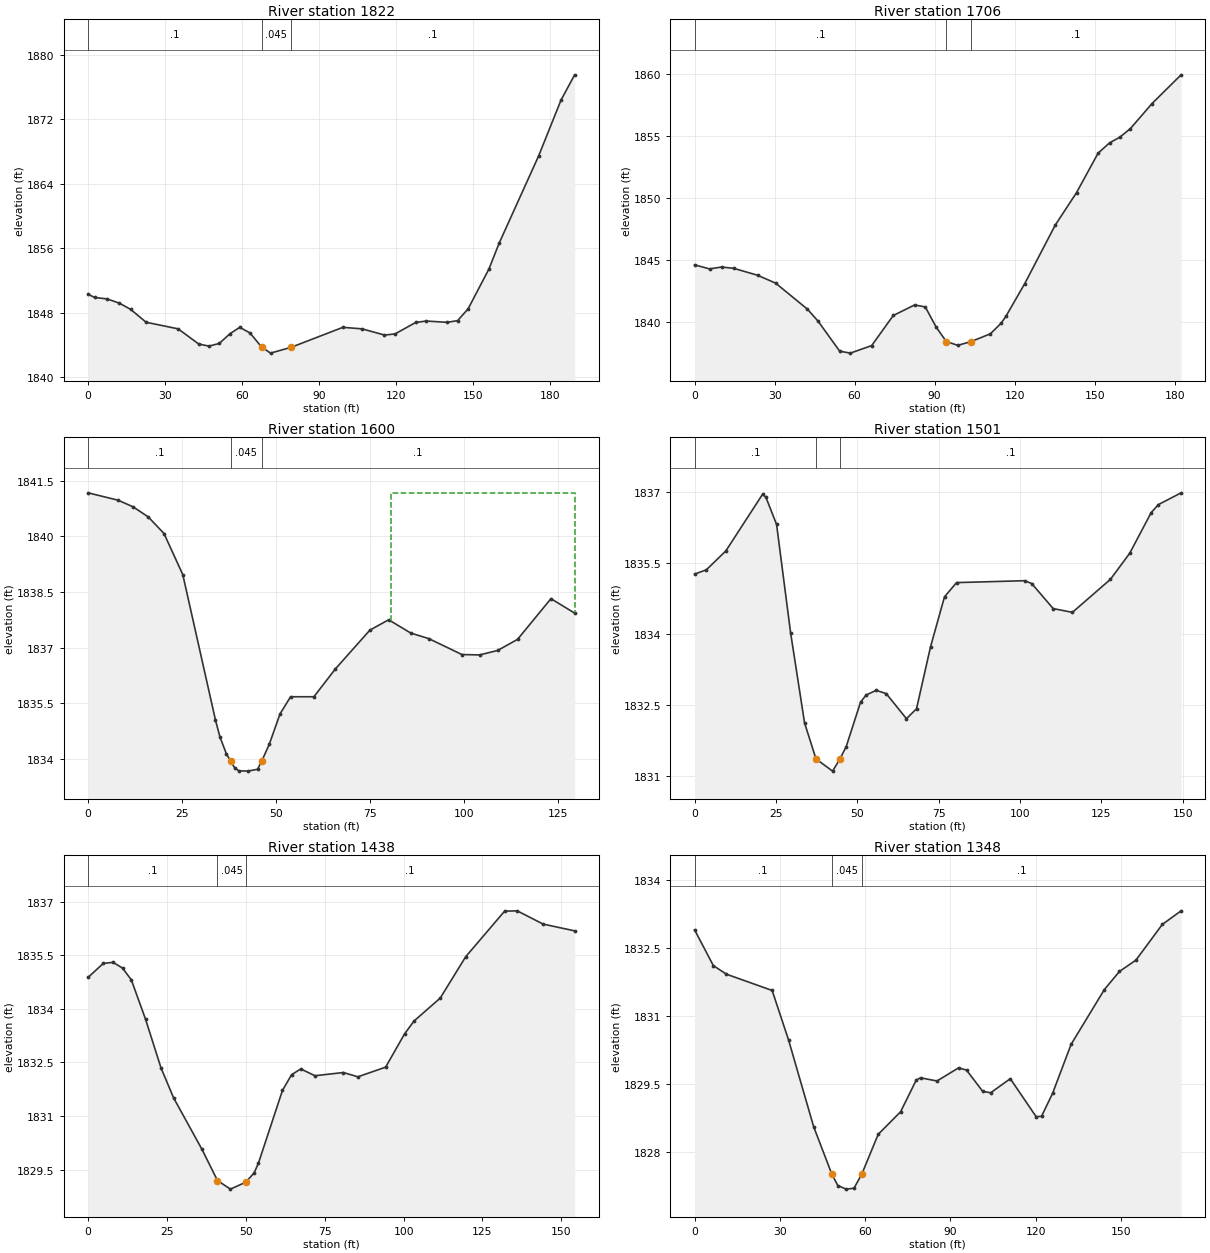
Type RM Length L Ch R = 1 ,1822    ,116.3,116.3,116.3
XS GIS Cut Line= 5
2195790.26450073656135.4920935182195812.54750267656151.508001164
2195878.70016469656154.9897202182195939.28207623656143.848219246
2195973.40292295  656147.3299383
#Sta/Elev= 30
       0 1850.32     2.6 1849.92     7.3 1849.75    12.2 1849.22    16.6 1848.44
    22.6 1846.85    35.1 1846.03    43.1 1844.15    47.1 1843.89    51.1 1844.22
    55.3 1845.43    59.1 1846.22    63.1 1845.52    67.6 1843.78    71.1 1843.02
    79.1 1843.74    99.3 1846.22   106.8 1846.03   115.5 1845.26   119.6  1845.4
   127.7 1846.83   131.8    1847   139.9 1846.84     144 1847.05   148.1 1848.52
   156.2 1853.45   160.2 1856.67   175.6  1867.5   184.3 1874.41   189.6 1877.54
#Mann= 3 ,-1,0
       0      .1       0    67.6    .045       0    79.1      .1       0
Bank Sta=67.6,79.1
XS Rating Curve= 0 ,0
Exp/Cntr(USF)=0,0
Exp/Cntr=0.3,0.1

Type RM Length L Ch R = 1 ,1706    ,105.6,105.6,105.6
XS GIS Cut Line= 5
2195762.15284319656228.2519665762195779.56143846656261.676469491
2195824.12744234656265.8545323552195871.47882147656273.514314273
2195923.00826346 656280.47775238
#Sta/Elev= 30
       0 1844.59     5.6 1844.26    10.1 1844.41    14.6 1844.31    23.6 1843.75
    30.4 1843.11    42.3 1841.01    46.3 1840.04    54.4 1837.62    58.4 1837.46
    66.4 1838.07    74.5  1840.5    82.5 1841.35    86.5 1841.19    90.6 1839.55
    94.4 1838.39    98.7 1838.09   103.71838.396   110.9 1839.02   114.9 1839.87
   116.8 1840.46   123.8 1843.08   135.2 1847.79   143.2 1850.42   151.3 1853.61
   155.6 1854.44   159.4 1854.89   163.4 1855.59   171.5 1857.61   182.4 1859.93
#Mann= 3 ,-1,0
       0      .1       0    94.4    .045       0   103.7      .1       0
Bank Sta=94.4,103.7
XS Rating Curve= 0 ,0
Exp/Cntr(USF)=0,0
Exp/Cntr=0.3,0.1

Type RM Length L Ch R = 1 ,1600    ,99.2,99.2,99.2
XS GIS Cut Line= 4
2195739.17349743656281.1740961912195740.56618505656300.671722891
2195783.04315751656357.7719153712195803.93347183656390.500074475
#Sta/Elev= 30
       0 1841.18       8 1840.98      12  1840.8      16 1840.53    20.2 1840.08
    25.2 1838.97    33.9 1835.04    35.1 1834.58    36.8 1834.13      381833.923
      39 1833.75    40.1 1833.67    42.5 1833.66    45.1 1833.71    46.2 1833.93
    48.2 1834.38    51.1 1835.21    53.9 1835.67    60.1 1835.67    65.8 1836.42
      75 1837.47      80 1837.75    85.9 1837.39    90.7 1837.24    99.5 1836.81
   104.2  1836.8     109 1836.92   114.3 1837.22   123.2 1838.32   129.5 1837.93
#Mann= 3 ,-1,0
       0      .1       0      38    .045       0    46.2      .1       0
#XS Ineff= 2 , 0
                           80.61         1841.17
Permanent Ineff=
       F       F
Bank Sta=38,46.2
XS Rating Curve= 0 ,0
Exp/Cntr(USF)=0,0
Exp/Cntr=0.3,0.1

Type RM Length L Ch R = 1 ,1501    ,63,63,63
XS GIS Cut Line= 3
2195648.79045244656376.065163392 2195731.1400715 656408.77939562
2195784.15968925656438.673435414
#Sta/Elev= 30
       0 1835.27     3.6 1835.36     9.6 1835.76    20.9 1836.96    21.9  1836.9
    25.2 1836.32    29.5 1834.03    33.8 1832.12    37.3 1831.36    42.4  1831.1
    44.61831.349    46.6 1831.62      51 1832.56    52.7 1832.71    55.8 1832.81
    58.9 1832.74    65.1 1832.21    68.2 1832.42    72.5 1833.73    76.8 1834.79
    80.5 1835.09   101.4 1835.13   103.6 1835.07   110.2 1834.54   116.1 1834.46
   127.8 1835.16   133.7 1835.71   140.3 1836.57   142.5 1836.74   149.5 1836.99
#Mann= 3 ,-1,0
       0      .1       0    37.3    .045       0    44.6      .1       0
Bank Sta=37.3,44.6
XS Rating Curve= 0 ,0
Exp/Cntr(USF)=0,0
Exp/Cntr=0.3,0.1

Type RM Length L Ch R = 1 ,1438    ,90.5,90.5,90.5
XS GIS Cut Line= 3
2195627.92102844656430.7768966012195722.11545571656478.156129482
2195770.05872708656487.180745269
#Sta/Elev= 29
       0 1834.88     4.8 1835.27     7.9  1835.3    10.9 1835.14    13.7 1834.81
    18.2 1833.71    23.1 1832.35    27.1 1831.51    36.1 1830.07      41  1829.2
    45.1 1828.96    49.9 1829.15    52.6 1829.41      54 1829.69    61.6 1831.72
    64.5 1832.16    67.4 1832.32    71.9 1832.13    80.9 1832.22    85.5  1832.1
    94.3 1832.37   100.3  1833.3   103.3 1833.66   111.6  1834.3   119.7 1835.46
     132 1836.73     136 1836.74   144.2 1836.37   154.2 1836.18
#Mann= 3 ,-1,0
       0      .1       0      41    .045       0    49.9      .1       0
Bank Sta=41,49.9
XS Rating Curve= 0 ,0
Exp/Cntr(USF)=0,0
Exp/Cntr=0.3,0.1

Type RM Length L Ch R = 1 ,1348    ,86.5,86.5,86.5
XS GIS Cut Line= 4
2195598.48292813  656478.70116022195594.37108756656504.194571721
2195685.08821757656590.3993938352195702.62417412656600.478761591
#Sta/Elev= 30
       0  1832.9     6.6 1832.11    11.2 1831.92    27.3 1831.56    33.1 1830.46
    41.9 1828.55    48.3  1827.5    50.4 1827.25    53.3 1827.17    56.1 1827.19
    58.9 1827.51    64.6 1828.38    72.5 1828.88      78 1829.58    79.5 1829.63
    85.3 1829.56    92.9 1829.85    95.7  1829.8   101.4 1829.33   104.2  1829.3
   111.1 1829.61   120.2 1828.77   122.1 1828.78     126 1829.29   132.5 1830.37
   144.2 1831.58   149.5 1831.98   155.3 1832.23   164.6 1833.02   171.2 1833.32
#Mann= 3 ,-1,0
       0      .1       0    48.3    .045       0    58.9      .1       0
Bank Sta=48.3,58.9
XS Rating Curve= 0 ,0
Exp/Cntr(USF)=0,0
Exp/Cntr=0.3,0.1