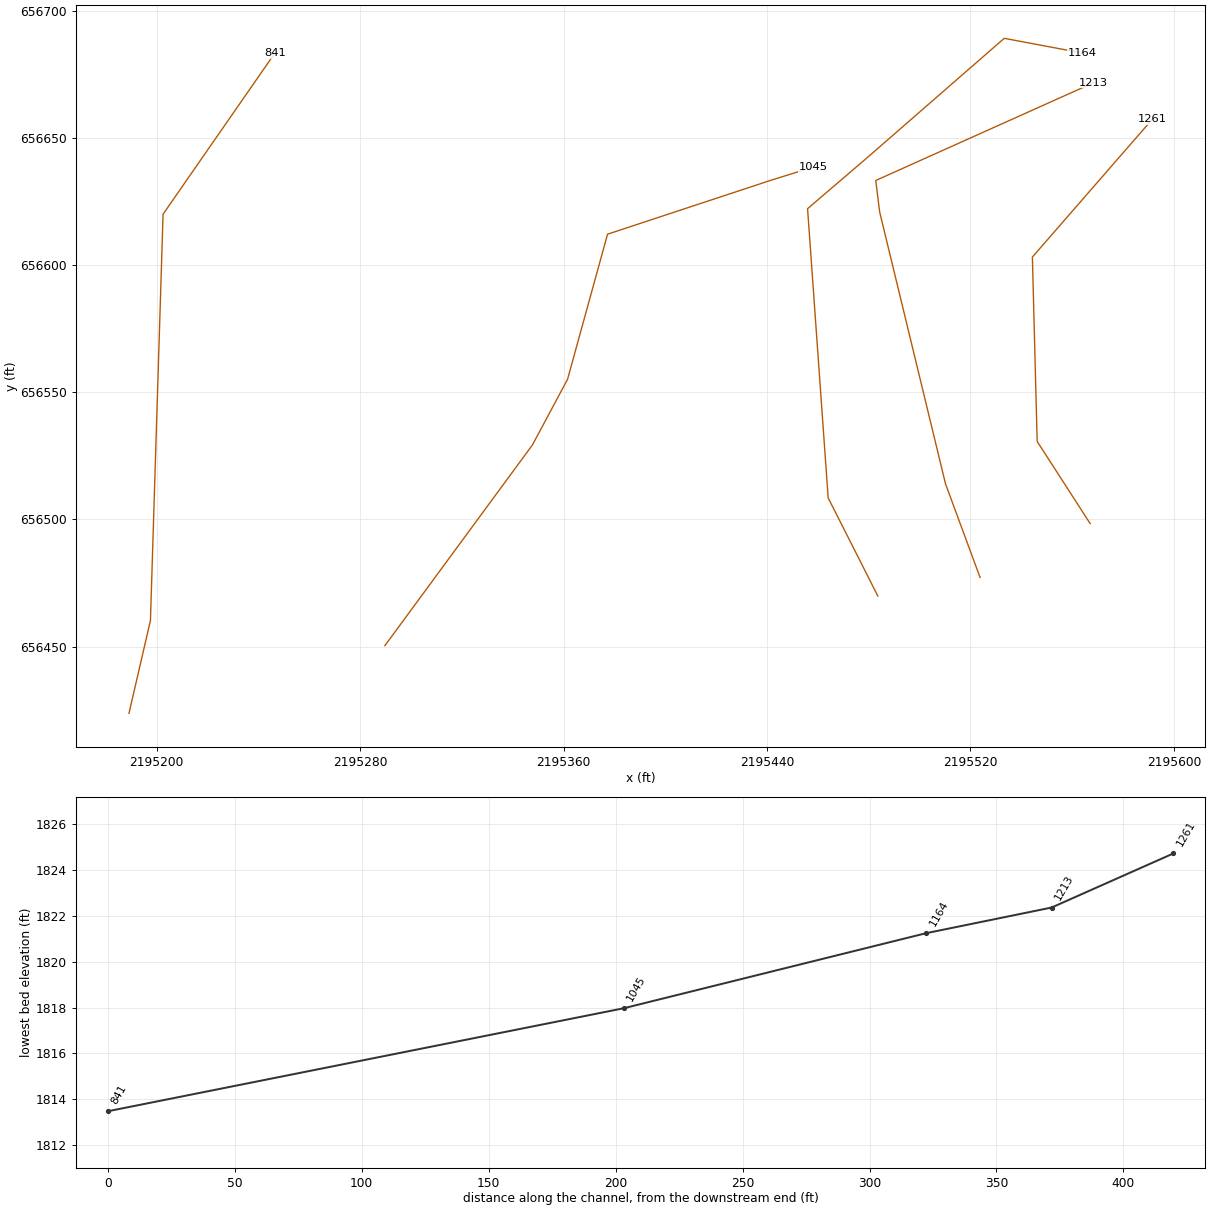
HEC-RAS study HERODSRN.prj: HERODSRN

--- HERODSRN.g01 (geometry) --- (continued)

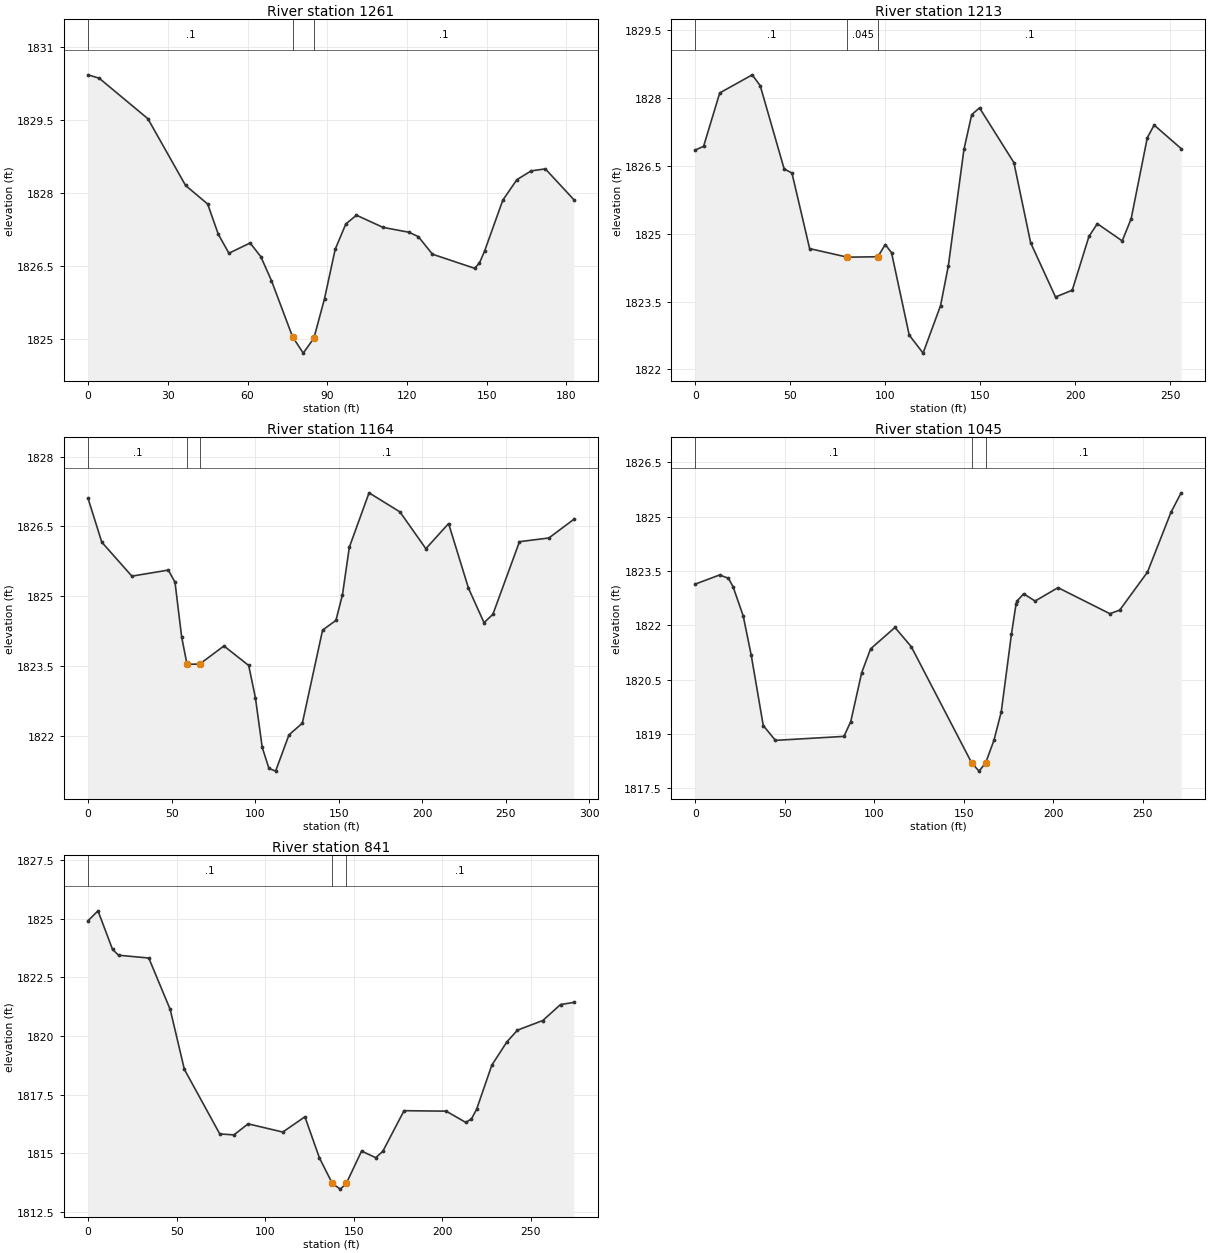
Type RM Length L Ch R = 1 ,1261    ,48,48,48
XS GIS Cut Line= 4
2195567.07958402656498.3127366022195546.22538905656530.617476888
2195544.34375666656603.117291852 2195591.5289603656657.298828883
#Sta/Elev= 29
       0 1830.43     4.2 1830.36    22.5 1829.53    36.7 1828.16      45 1827.78
      49 1827.16      53 1826.77      61 1826.98      65  1826.7      69 1826.21
      77 1825.05      81 1824.72      85 1825.03      89 1825.84      93 1826.85
      97 1827.37     101 1827.55     111  1827.3   120.8  1827.2   124.3 1827.11
   129.6 1826.75   145.5 1826.46   147.3 1826.57   149.2 1826.81   156.1 1827.86
   161.4 1828.28   166.8 1828.46   172.1  1828.5   182.8 1827.87
#Mann= 3 ,-1,0
       0      .1       0      77    .045       0      85      .1       0
Bank Sta=77,85
XS Rating Curve= 0 ,0
Exp/Cntr(USF)=0,0
Exp/Cntr=0.3,0.1

Type RM Length L Ch R = 1 ,1213    ,49.5,49.5,49.5
XS GIS Cut Line= 5
2195523.76141075656477.1580247482195510.18613246656513.918669079
2195484.28153688656620.8265238452195482.74026215656633.210115322
2195568.42577843  656671.6542727
#Sta/Elev= 30
       0 1826.85     4.3 1826.93    12.8 1828.11    29.9 1828.51    34.1 1828.27
    46.7 1826.43    50.8 1826.34    60.1 1824.67      80 1824.48      96 1824.49
    99.9 1824.76   103.2 1824.58   112.5 1822.76   119.8 1822.36     129 1823.41
   133.1 1824.29   141.3 1826.86   145.4 1827.63   149.5 1827.78   167.6 1826.57
   176.4  1824.8   189.5  1823.6   198.3 1823.75   207.1 1824.94   211.5 1825.22
   224.6 1824.84   229.3 1825.33   237.8 1827.12   241.4  1827.4   255.6 1826.88
#Mann= 3 ,-1,0
       0      .1       0      80    .045       0      96      .1       0
Bank Sta=80,96
XS Rating Curve= 0 ,0
Exp/Cntr(USF)=0,0
Exp/Cntr=0.3,0.1

Type RM Length L Ch R = 1 ,1164    ,119,119,119
XS GIS Cut Line= 6
2195483.56983189656469.8383737282195464.03550606656508.414390353
2195455.92936848656622.1178998182195479.93077494656642.650879992
 2195533.2708235 656689.089001312195563.77203676656683.370023825
#Sta/Elev= 30
       0  1827.1     8.2 1826.16    26.2 1825.43      48 1825.56      52  1825.3
      56 1824.12    59.21823.536   66.76 1823.54    81.3 1823.93    96.1 1823.51
   100.1 1822.82   104.2 1821.75   108.2  1821.3   112.2 1821.24   120.2 1822.02
   128.2 1822.27   140.3 1824.27   148.3 1824.48   152.2 1825.03   156.3 1826.05
   168.1 1827.22   186.6 1826.81   202.1 1826.02   215.7 1826.56   227.6 1825.17
   236.9 1824.43   242.2 1824.61   258.1 1826.17   275.7 1826.25   290.6 1826.65
#Mann= 3 ,-1,0
       0      .1       0    59.2    .045       0   66.76      .1       0
Bank Sta=59.2,66.76
XS Rating Curve= 0 ,0
Exp/Cntr(USF)=0,0
Exp/Cntr=0.3,0.1

Type RM Length L Ch R = 1 ,1045    ,203.2,203.2,203.2
XS GIS Cut Line= 6
2195289.70054712656450.3370094832195347.72919802656529.255974699
2195361.52955946656555.0345853192195377.27130201656612.096900731
2195441.38651641656633.2537838352195458.07830537656638.449157159
#Sta/Elev= 30
       0 1823.14    13.5 1823.39    18.4  1823.3      21 1823.07    26.7 1822.26
    31.2 1821.17    37.9 1819.23    44.7 1818.82      83 1818.93    86.8 1819.34
    92.9 1820.69    97.9 1821.35   111.5 1821.94   120.6 1821.41   154.41818.195
   158.5 1817.97   162.21818.202   166.8 1818.82   170.9 1819.61   176.6 1821.76
   179.2  1822.6   179.9 1822.68   183.4 1822.87   189.8 1822.67   202.6 1823.04
   231.6 1822.32   237.1 1822.42   252.6 1823.47   265.7 1825.12   271.4 1825.66
#Mann= 3 ,-1,0
       0      .1       0   154.4    .045       0   162.2      .1       0
Bank Sta=154.4,162.2
XS Rating Curve= 0 ,0
Exp/Cntr(USF)=0,0
Exp/Cntr=0.3,0.1

Type RM Length L Ch R = 1 ,841     ,,,
XS GIS Cut Line= 4
2195189.05143525656423.7203335952195197.50273194656460.253626899
2195202.46704629656619.9646036352195246.42730911656683.283842896
#Sta/Elev= 30
       0 1824.91     5.6 1825.33    13.8 1823.69    17.2 1823.44    34.3 1823.32
    46.4 1821.13    54.4 1818.58    74.4 1815.83    82.4 1815.79    90.4 1816.26
     110 1815.91   122.5 1816.56   130.7 1814.81     138 1813.72   142.5 1813.48
   145.91813.726   154.5  1815.1   162.5 1814.82   166.5 1815.09   178.5 1816.82
   202.3  1816.8   213.4 1816.32   216.6 1816.47   219.5 1816.88   228.1 1818.76
   236.7 1819.76   242.6 1820.25   256.9 1820.66   266.9 1821.34   274.4 1821.43
#Mann= 3 ,-1,0
       0      .1       0     138    .045       0   145.9      .1       0
Bank Sta=138,145.9
XS Rating Curve= 0 ,0
Exp/Cntr(USF)=0,0
Exp/Cntr=0.3,0.1
LCMann Table=0

Chan Stop Cuts=-1
Use User Specified Reach Order=0
Composite Channel Slope=5